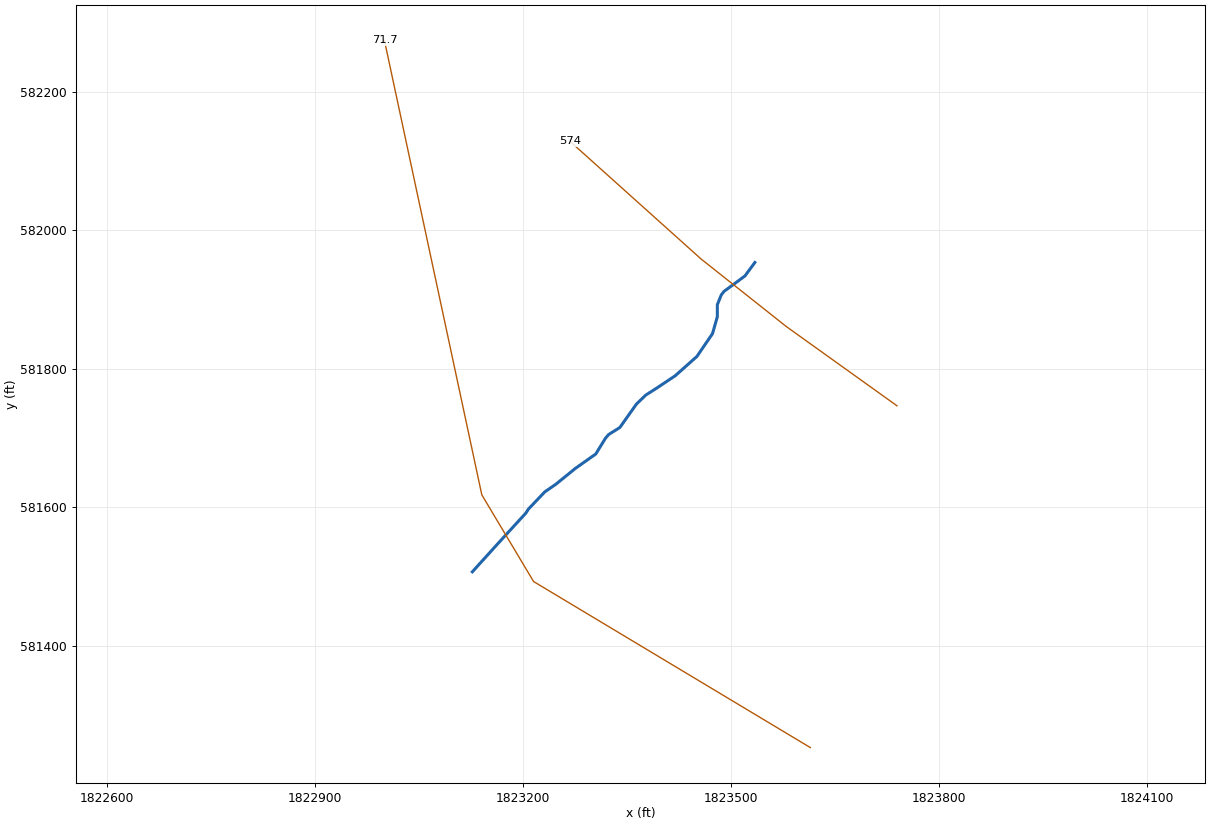
--- StrghtCrk.prj (project) ---

Proj Title=StrghtCrk
Current Plan=p01
Default Exp/Contr=0,0
English Units
Geom File=g01
Flow File=f01
Plan File=p01
BEGIN DESCRIPTION:
AMEC Environment & Infrastructure, 2013
Projection: NAD 1983 State Plane West Virginia South FIPS 4702 (US Feet)
Vertical Datum: NAVD 1988
END DESCRIPTION:
DSS Export Rating Curves= 0
DSS Export Rating Curve Sorted= 0
DSS Export Volume Flow Curves= 0
DXF OffsetX= 0
DXF OffsetY= 0
DXF ScaleX= 0
DXF ScaleY= 0

--- StrghtCrk.p01 (plan) ---

Plan Title=Floodplain
Program Version=4.00
Geom File=g01
Flow File=f01
K Sum by GR=0
Std Step Tol=0.01
Critical Tol=0.01
Num of Std Step Trials=20
Max Error Tol=0.3
Flow Tol Ratio=0.001
Split Flow NTrial=30
Split Flow Tol=0.02
Split Flow Ratio=0.02
Log Output Level=0
Friction Slope Method=1
Unsteady Friction Slope Method=2
Unsteady Bridges Friction Slope Method=1
Global Log Level=0
CheckData=False
Run HTab=0
Run UNet=0
Run PostProcess=0
UNET Theta=0
UNET Theta Warmup=0
UNET ZTol=0
UNET ZSATol=0
UNET MxIter=0
UNET MaxInSteps=0
UNET DtIC=0
UNET DtMin=0
UNET MaxCRTS=0
UNET WFStab=0
UNET SFStab=0
UNET WFX=0
UNET SFX=0
UNET DSS MLevel=0
UNET DZMax Abort=0
UNET Convert EG Bridges=0
UNET Use Existing IB Tables=0
UNET Froude Limit=0
UNET Froude Power=0
Write IC File=0
Echo Input=False
Echo Output=False
Write Detailed=0

--- StrghtCrk.f01 (steady flow) ---

Flow Title=NFF Regression Equation
Program Version=4.00
Number of Profiles=1
Profile Names=P100yr
River Rch & RM=StrghtCrk,Main      ,574
891.6806
River Rch & RM=StrghtCrk,Main      ,71.7
894.6682
Boundary for River Rch & Prof#=StrghtCrk,Main      ,1
Up Type=0
Dn Type=3
Dn Slope=0.013576

--- StrghtCrk.g01 (geometry) ---

Geom Title=USGS 3m DEM
Program Version=4.10

River Reach=StrghtCrk       ,Main
Reach XY= 26
     1823534.775      581953.396     1823534.775      581953.396
     1823520.549      581934.102     1823506.656      581923.681
     1823490.353      581911.823     1823486.226      581906.469
     1823480.607       581892.42     1823480.608      581875.053
     1823473.663      581850.739     1823451.088      581817.741
     1823419.828      581789.952     1823393.779      581772.584
     1823377.221      581761.939     1823363.978      581749.203
     1823339.945      581715.271     1823323.784      581705.169
     1823319.106       581699.64     1823305.214      581677.062
     1823275.691      581656.221     1823247.905      581633.643
     1823231.641      581622.381     1823208.039      581597.597
      1823204.49       581591.96     1823166.285      581550.278
     1823127.183       581507.14     1823127.183       581507.14

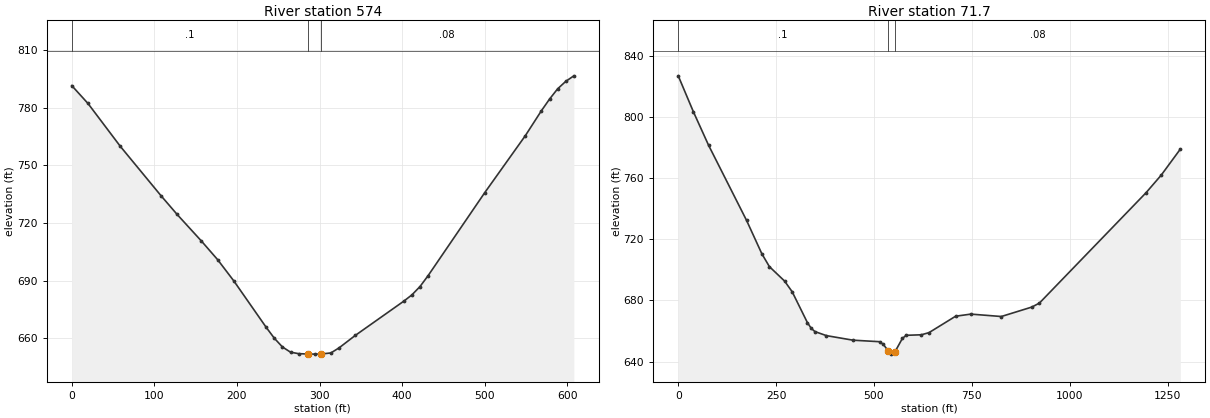
Type RM Length L Ch R = 1 ,574     ,510,502.2,493.5
XS GIS Cut Line= 4
     1823739.791      581746.607     1823580.197      581860.897
     1823457.371      581958.218     1823267.569      582128.552
#Sta/Elev= 30
       0  791.46    19.6  782.18    58.9  759.78     108  734.18   127.6  724.39
     157  710.55   176.7  700.82   196.3  689.75   235.5  665.59   245.3  659.95
   255.1  655.41   264.9   652.7   274.6  651.93   286.4  651.72   294.2  651.68
   301.4  651.71   313.8   652.3   323.6  654.91   343.2  661.38     402  679.23
   411.9  682.52   421.7  686.86   431.5  692.52   500.1  735.74   549.2  765.36
   568.8  778.43   578.6  784.46   588.4   789.8   598.2  793.66     608  796.55
#Mann= 3 , 0 , 0
       0      .1       0   286.4    .045       0   301.4     .08       0
Bank Sta=286.4,301.4
XS Rating Curve= 0 ,0
Exp/Cntr=0.3,0.1

Type RM Length L Ch R = 1 ,71.7    ,64.9,71.7,78.6
XS GIS Cut Line= 4
     1823614.791      581253.552     1823215.486      581493.135
     1823140.833      581618.135     1823000.208      582274.385
#Sta/Elev= 30
       0  827.08    38.8  803.49    77.6  781.56   174.6  732.38   213.4  710.65
   232.8  702.16   271.6  692.71     291  685.71   329.8  665.55   339.6  661.77
   349.2  659.62   378.4  656.98   446.3  653.99   514.2     653   523.9  651.24
   536.3     647   543.3  644.86     553   646.1   572.4   655.1   582.1  657.18
     621  657.53   640.4  658.92   708.5  669.68   747.4  671.06   825.2  669.49
   903.1  675.67   922.5  678.28  1194.9  750.55  1233.8  762.11  1282.4  779.08
#Mann= 3 , 0 , 0
       0      .1       0   536.3    .045       0     553     .08       0
Bank Sta=536.3,553
XS Rating Curve= 0 ,0
Exp/Cntr=0.3,0.1

Chan Stop Cuts=-1
Use User Specified Reach Order=0
Composite Channel Slope=5